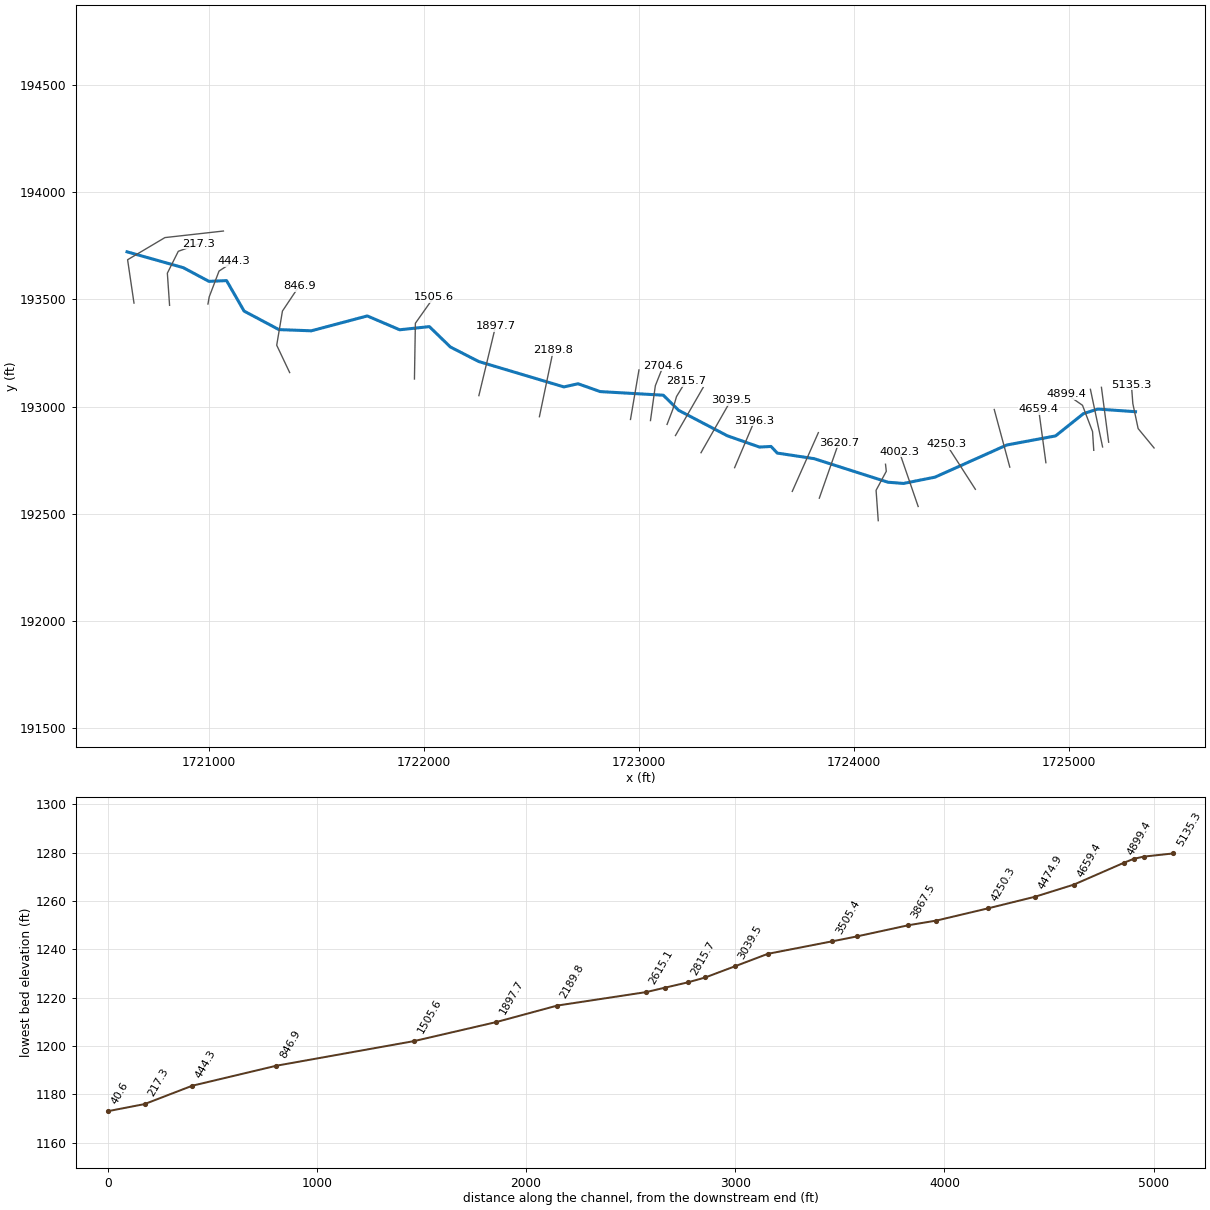
--- Riffe Branch.prj (project) ---

Proj Title=Riffe Branch
Current Plan=p01
Default Exp/Contr=0,0
English Units
Geom File=g01
Flow File=f01
Plan File=p01
BEGIN DESCRIPTION:
END DESCRIPTION:
DSS Export Rating Curves= 0
DSS Export Rating Curve Sorted= 0
DSS Export Volume Flow Curves= 0
DXF OffsetX= 0
DXF OffsetY= 0
DXF ScaleX= 0
DXF ScaleY= 0

--- Riffe Branch.p01 (plan) ---

Plan Title=Floodplain
Program Version=4.00
Geom File=g01
Flow File=f01
K Sum by GR=0
Std Step Tol=0.01
Critical Tol=0.01
Num of Std Step Trials=20
Max Error Tol=0.3
Flow Tol Ratio=0.001
Split Flow NTrial=30
Split Flow Tol=0.02
Split Flow Ratio=0.02
Log Output Level=0
Friction Slope Method=1
Unsteady Friction Slope Method=2
Unsteady Bridges Friction Slope Method=1
Global Log Level=0
CheckData=False
Run HTab=0
Run UNet=0
Run PostProcess=0
UNET Theta=0
UNET Theta Warmup=0
UNET ZTol=0
UNET ZSATol=0
UNET MxIter=0
UNET MaxInSteps=0
UNET DtIC=0
UNET DtMin=0
UNET MaxCRTS=0
UNET WFStab=0
UNET SFStab=0
UNET WFX=0
UNET SFX=0
UNET DSS MLevel=0
UNET DZMax Abort=0
UNET Convert EG Bridges=0
UNET Use Existing IB Tables=0
UNET Froude Limit=0
UNET Froude Power=0
Write IC File=0
Echo Input=False
Echo Output=False
Write Detailed=0

--- Riffe Branch.f01 (steady flow) ---

Flow Title=NFF Regression Equation
Program Version=4.00
Number of Profiles=1
Profile Names=P100yr
River Rch & RM=Riffe Branch,Main      ,5135.3
557.5255
River Rch & RM=Riffe Branch,Main      ,3620.7
581.0772
River Rch & RM=Riffe Branch,Main      ,3505.4
727.8007
River Rch & RM=Riffe Branch,Main      ,2615.1
788.3495
River Rch & RM=Riffe Branch,Main      ,217.3
841.0143
Boundary for River Rch & Prof#=Riffe Branch,Main      ,1
Up Type=0
Dn Type=3
Dn Slope=0.023461

--- Riffe Branch.g01 (geometry) ---

Geom Title=Geometry
Program Version=4.00

River Reach=Riffe Branch    ,Main
Reach XY= 30
     1725309.812      192976.015     1725133.965      192988.397
     1725067.307      192966.904     1724937.737      192863.178
     1724710.688      192820.854     1724377.119      192670.977
     1724230.897      192641.732     1724158.265      192647.302
     1723814.133       192757.34     1723643.118      192783.273
     1723614.382      192814.112     1723560.414      192811.308
     1723411.141      192863.807     1723184.288      192982.614
     1723113.214      193052.982     1722819.633      193069.842
     1722716.554      193106.379     1722650.671       193091.66
      1722254.16       193210.17      1722122.56      193277.798
     1722024.785      193372.713     1721886.712      193357.995
     1721736.022      193422.476     1721475.678      193353.197
     1721325.057        193358.8     1721162.979      193445.039
       1721081.4      193587.183     1720999.397      193583.679
     1720880.247      193647.459     1720618.314      193721.431

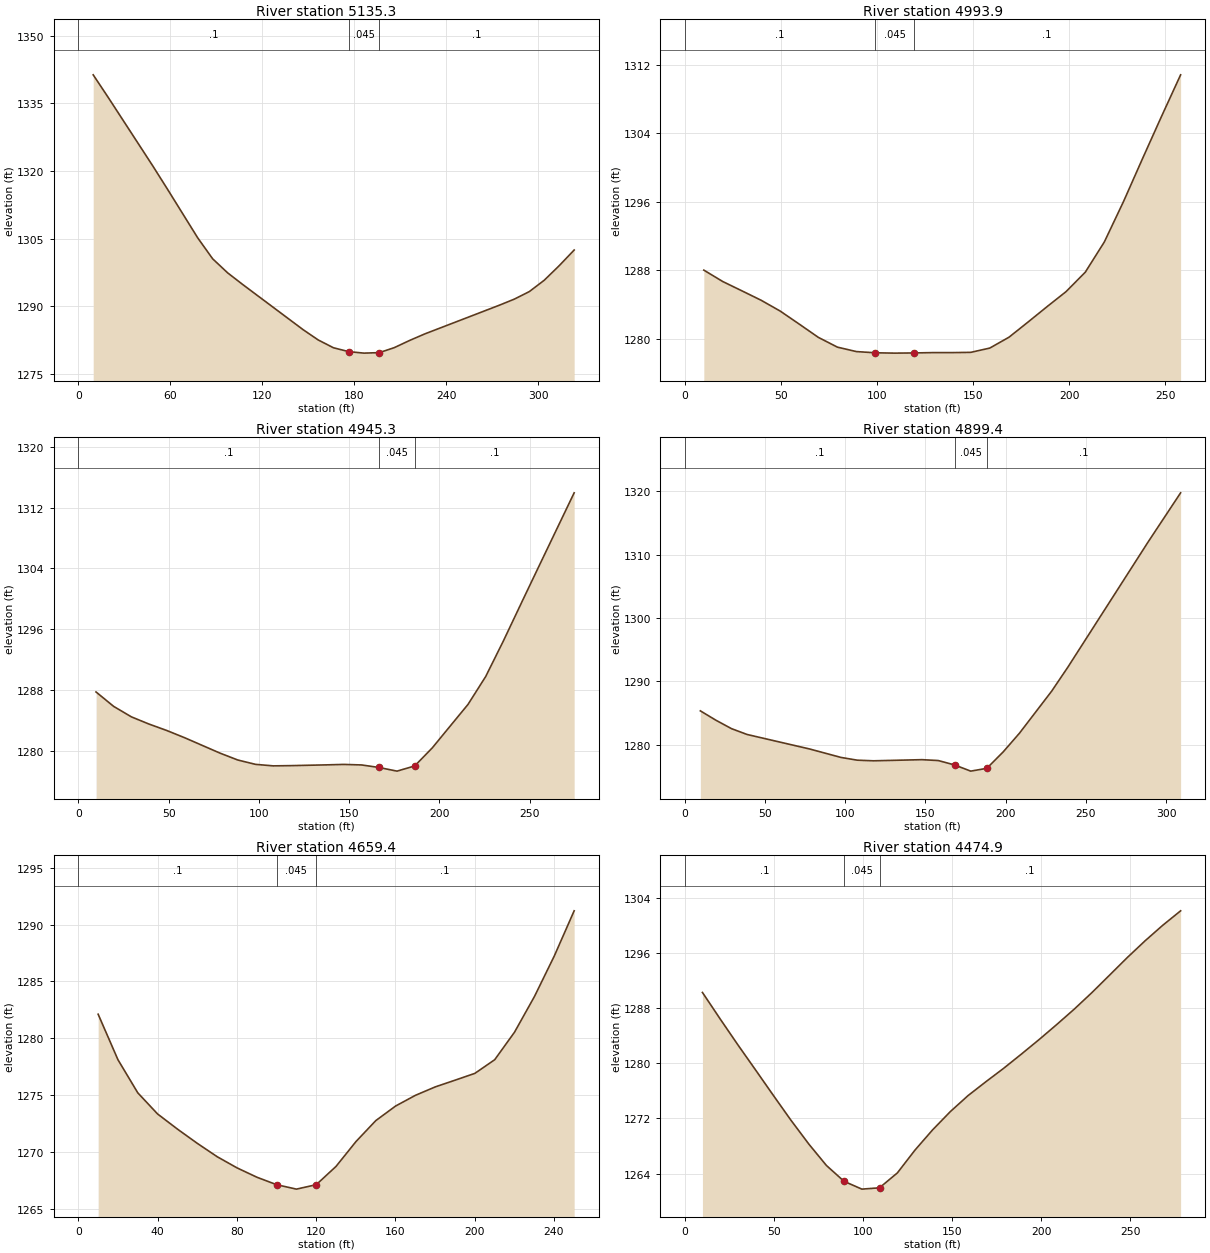
Type RM Length L Ch R = 1 ,5135.3  ,142.9,141.4,141.1
XS GIS Cut Line= 4
     1725396.103      192807.146     1725321.989      192897.463
     1725297.336      193013.948     1725290.802      193101.164
#Sta/Elev= 23
     9.7  1341.3    19.5 1336.29    48.7 1321.05    58.4 1315.83    77.9 1305.17
    87.6 1300.55    97.4 1297.43   107.1 1294.88   146.6 1284.85   156.5 1282.56
   166.4 1280.84   176.3 1279.98   186.3 1279.65   196.3 1279.76   206.1 1280.87
   216.1 1282.46     226 1283.91   274.8 1290.29   284.5 1291.63   294.2 1293.29
   303.9  1295.8   313.6    1299   323.4 1302.49
#Mann= 3 , 0 , 0
       0      .1       0   176.3    .045       0   196.3      .1       0
Bank Sta=176.3,196.3
XS Rating Curve= 0 ,0
Exp/Cntr=0.3,0.1

Type RM Length L Ch R = 1 ,4993.9  ,46.8,48.6,49.2
XS GIS Cut Line= 2
     1725184.842      192833.989     1725151.257      193089.758
#Sta/Elev= 27
     9.9 1288.03    19.8 1286.69    29.8  1285.6    39.7 1284.51    49.6 1283.25
    59.5 1281.73    69.5 1280.17    79.4 1279.03    89.3 1278.51    99.1 1278.37
    99.2 1278.37   109.1 1278.33   119.1 1278.35     129 1278.39   138.9 1278.39
   148.8 1278.42   158.7 1278.92   168.7 1280.19   178.6 1281.96   188.5 1283.76
   198.4 1285.52   208.4 1287.79   218.3 1291.32   228.2    1296   238.1 1301.02
     248 1305.96     258 1310.85
#Mann= 3 , 0 , 0
       0      .1       0    99.1    .045       0   119.1      .1       0
Bank Sta=99.1,119.1
XS Rating Curve= 0 ,0
Exp/Cntr=0.3,0.1

Type RM Length L Ch R = 1 ,4945.3  ,41.6,45.9,50.2
XS GIS Cut Line= 2
     1725156.665      192811.715     1725100.004      193080.398
#Sta/Elev= 30
     9.8  1287.8    19.6  1285.9    29.4 1284.53    39.2 1283.58      49 1282.74
    58.8  1281.8    68.6 1280.79    78.5 1279.77    88.3 1278.87    98.1  1278.3
   107.9  1278.1   117.7 1278.13   127.5 1278.18   137.3 1278.23   147.1 1278.29
   156.9 1278.22   166.5 1277.89   166.7 1277.88   176.5 1277.41   186.3 1278.09
   186.5 1278.14   196.1 1280.48   205.9 1283.31   215.8 1286.16   225.6 1289.82
   235.4 1294.49   245.2 1299.39     255 1304.25   264.8 1309.09   274.6 1313.93
#Mann= 3 , 0 , 0
       0      .1       0   166.5    .045       0   186.5      .1       0
Bank Sta=166.5,186.5
XS Rating Curve= 0 ,0
Exp/Cntr=0.3,0.1

Type RM Length L Ch R = 1 ,4899.4  ,246.2,240.1,233.9
XS GIS Cut Line= 4
      1725115.54      192796.179     1725109.974      192883.288
     1725063.134      193005.936     1724989.004      193057.718
#Sta/Elev= 19
     9.7 1285.33    19.4 1283.85    29.1 1282.52    38.8  1281.6    77.6 1279.32
    97.4 1277.97   107.5 1277.54   117.6 1277.44   147.9 1277.62     158 1277.48
   168.2 1276.78   178.2 1275.81   188.2 1276.25   198.4 1278.84   208.5 1281.78
   228.6 1288.43   238.7 1292.22   288.9 1312.07     309 1319.77
#Mann= 3 , 0 , 0
       0      .1       0   168.2    .045       0   188.2      .1       0
Bank Sta=168.2,188.2
XS Rating Curve= 0 ,0
Exp/Cntr=0.3,0.1

Type RM Length L Ch R = 1 ,4659.4  ,181.2,184.5,187.8
XS GIS Cut Line= 2
     1724892.904      192738.398     1724859.318      192986.417
#Sta/Elev= 25
      10 1282.12      20 1278.12      30 1275.21      40 1273.35    50.1 1272.01
    60.1 1270.76    70.1 1269.59    80.1 1268.61    90.1 1267.79   100.1 1267.13
   110.1 1266.74   120.1 1267.13   130.1 1268.74   140.2 1270.93   150.2 1272.77
   160.2 1274.05   170.2 1274.99   180.2 1275.73   190.2 1276.32   200.2 1276.92
   210.2 1278.12   220.2 1280.54   230.3 1283.69   240.3 1287.25   250.3 1291.21
#Mann= 3 , 0 , 0
       0      .1       0   100.1    .045       0   120.1      .1       0
Bank Sta=100.1,120.1
XS Rating Curve= 0 ,0
Exp/Cntr=0.3,0.1

Type RM Length L Ch R = 1 ,4474.9  ,216.8,224.5,232.2
XS GIS Cut Line= 2
     1724724.974       192717.73     1724652.636      192986.417
#Sta/Elev= 29
     9.9 1290.28    19.9 1286.42    29.8 1282.68    39.8 1279.01    49.7 1275.35
    59.6 1271.74    69.6 1268.29    79.5 1265.18    89.4 1262.88    99.4 1261.75
   109.3 1261.94   109.4 1261.97   119.3  1264.1   129.2 1267.41   139.1 1270.35
   149.1 1273.01     159 1275.32   168.9 1277.31   178.9 1279.26   188.8 1281.31
   198.8 1283.43   208.7 1285.61   218.6 1287.86   228.6 1290.28   238.5 1292.81
   248.4 1295.35   258.4 1297.78   268.3 1300.03   278.3 1302.12
#Mann= 3 , 0 , 0
       0      .1       0    89.4    .045       0   109.4      .1       0
Bank Sta=89.4,109.4
XS Rating Curve= 0 ,0
Exp/Cntr=0.3,0.1

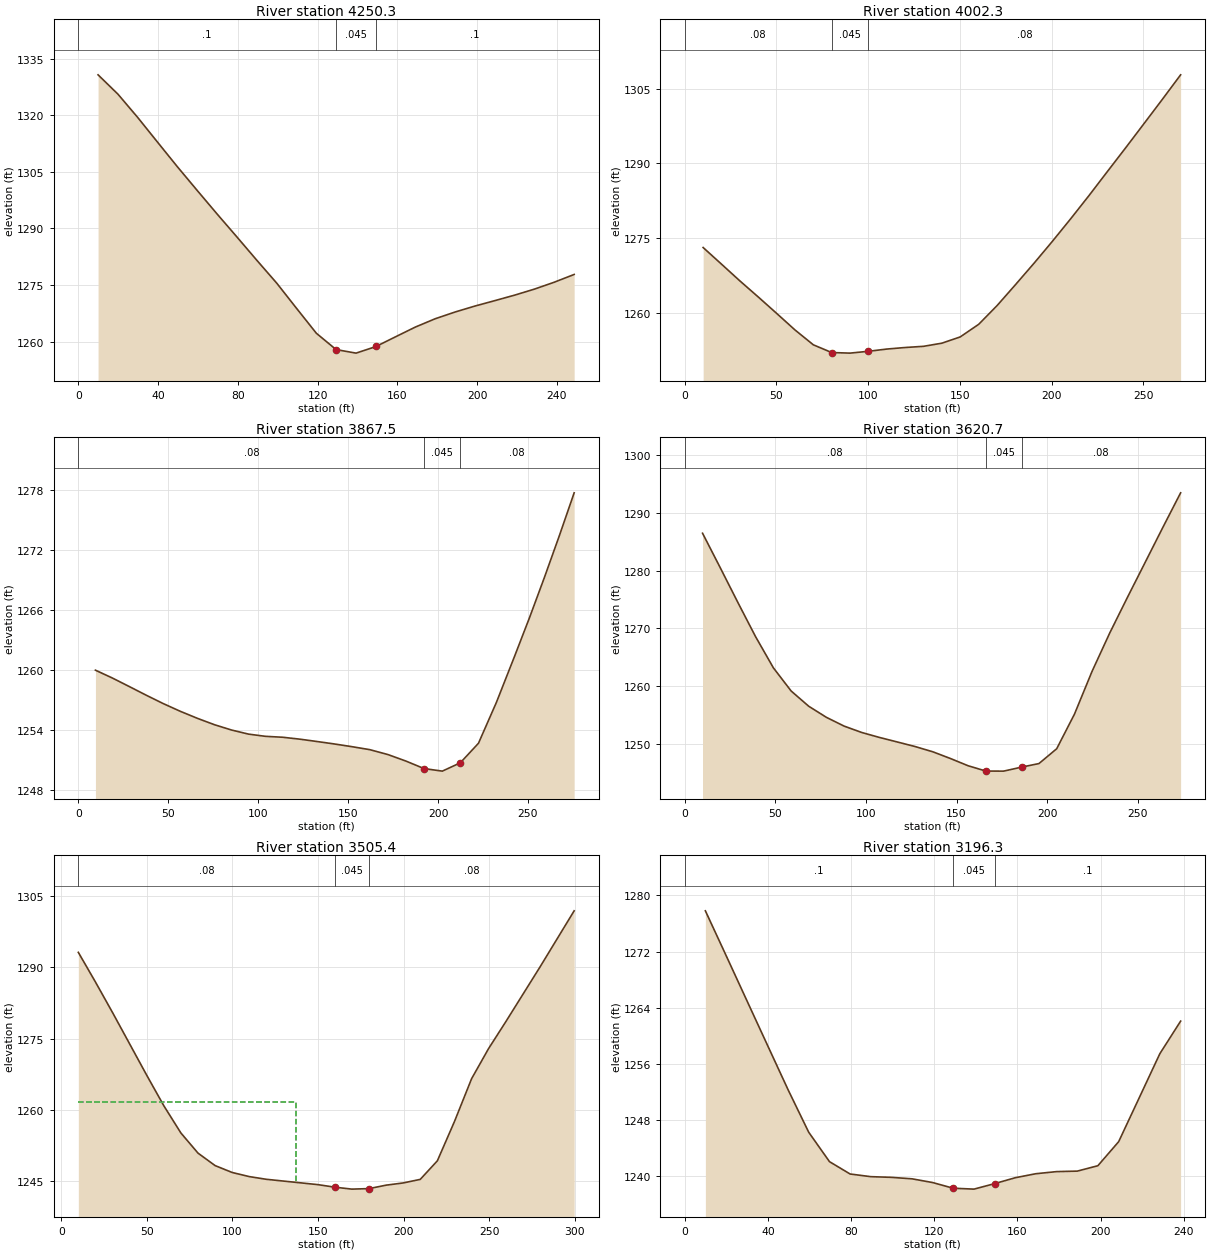
Type RM Length L Ch R = 1 ,4250.3  ,254,248.1,242.1
XS GIS Cut Line= 2
     1724564.796      192614.389     1724430.452      192823.654
#Sta/Elev= 26
     9.9 1330.71    19.9 1325.57    29.8  1319.4    39.8 1312.82    49.7 1306.34
    59.7 1300.02    69.6 1293.83    79.6 1287.71    89.5 1281.58    99.5 1275.51
   109.4 1268.86   119.4 1262.21   129.3 1257.89   139.3 1256.95   149.2 1258.68
   149.3 1258.71   159.2  1261.3   169.1 1263.87     179 1266.06     189 1267.85
   198.9 1269.42   208.9 1270.86   218.8 1272.31   228.8 1273.92   238.7 1275.74
   248.7  1277.8
#Mann= 3 , 0 , 0
       0      .1       0   129.3    .045       0   149.3      .1       0
Bank Sta=129.3,149.3
XS Rating Curve= 0 ,0
Exp/Cntr=0.3,0.1

Type RM Length L Ch R = 1 ,4002.3  ,155.6,134.8,113.9
XS GIS Cut Line= 2
     1724298.692      192534.299     1724210.852      192790.069
#Sta/Elev= 28
      10  1273.1      20 1269.76      30  1266.4    40.1 1263.14    50.1 1259.85
    60.1 1256.52    70.1 1253.53    80.1 1251.98    90.1 1251.86   100.1 1252.23
   100.2 1252.23   110.2 1252.68   120.2 1252.99   130.2 1253.23   140.2 1253.86
   150.2 1255.12   160.3 1257.66   170.3 1261.42   180.3 1265.61   190.3 1269.87
   200.3 1274.27   210.3 1278.81   220.4 1283.53   230.4 1288.35   240.4 1293.14
   250.4    1298   260.4 1302.88   270.4 1307.83
#Mann= 3 , 0 , 0
       0     .08       0    80.1    .045       0   100.1     .08       0
Bank Sta=80.1,100.1
XS Rating Curve= 0 ,0
Exp/Cntr=0.3,0.1

Type RM Length L Ch R = 1 ,3867.5  ,242.8,246.8,250.9
XS GIS Cut Line= 4
     1724113.006      192468.094     1724102.953      192609.746
     1724150.475      192698.393      1724146.82      192731.293
#Sta/Elev= 30
     9.5 1259.99    18.9 1259.21    28.4 1258.35    37.9 1257.48    47.3 1256.65
    56.8 1255.88    66.3 1255.18    75.7 1254.55    85.2 1254.02    94.7 1253.61
   104.1 1253.39   113.6  1253.3   123.1 1253.11   132.5 1252.88     142 1252.64
   152.1 1252.36   162.1 1252.06   172.2 1251.57   182.2 1250.92   192.3 1250.17
   192.4 1250.17   202.4 1249.92   212.4 1250.75   222.5  1252.7   232.5 1256.79
   242.6 1261.39   250.9 1265.24   259.1 1269.21   267.4 1273.37   275.7 1277.68
#Mann= 3 , 0 , 0
       0     .08       0   192.4    .045       0   212.4     .08       0
Bank Sta=192.4,212.4
XS Rating Curve= 0 ,0
Exp/Cntr=0.3,0.1

Type RM Length L Ch R = 1 ,3620.7  ,117.4,115.3,113.2
XS GIS Cut Line= 2
     1723838.824      192573.052     1723929.248      192831.405
#Sta/Elev= 30
     9.8 1286.48    19.6 1280.49    29.3 1274.49    39.1 1268.55    48.9 1263.17
    58.7 1259.16    68.4 1256.52    78.2 1254.59      88 1253.07    97.8 1251.96
   107.5 1251.11   117.3 1250.33   127.1 1249.54   136.9 1248.63   146.6 1247.47
   156.4 1246.21     166 1245.31   166.2 1245.29     176 1245.28   185.7 1245.96
     186 1245.98   195.5 1246.59   205.3 1249.16   215.1 1255.15   224.8 1262.55
   234.6 1269.22   244.4 1275.41   254.2 1281.48   263.9  1287.5   273.7 1293.48
#Mann= 3 , 0 , 0
       0     .08       0     166    .045       0     186     .08       0
Bank Sta=166,186
XS Rating Curve= 0 ,0
Exp/Cntr=0.3,0.1

Type RM Length L Ch R = 1 ,3505.4  ,309.9,309.1,307.9
XS GIS Cut Line= 2
     1723713.022      192604.652     1723834.448      192878.506
#Sta/Elev= 25
      10 1293.13      20 1286.89      30 1280.45    49.9  1267.3    59.9 1260.87
    69.9 1255.12    79.9 1250.88    89.9 1248.25    99.9  1246.8   109.8 1245.94
   119.8 1245.37   149.8 1244.25   159.8 1243.71   169.8  1243.3   179.8 1243.41
   189.7 1244.13   199.7  1244.6   209.7 1245.35   219.7 1249.26   229.7 1257.53
   239.7 1266.54   249.6 1272.87   259.6 1278.49   279.6 1290.02   299.6 1301.87
#Mann= 3 , 0 , 0
      10     .08       0   159.8    .045       0   179.8     .08       0
#XS Ineff= 2 , 0
          137.42  1261.7
Permanent Ineff=
       F       F
Bank Sta=159.8,179.8
XS Rating Curve= 0 ,0
Exp/Cntr=0.3,0.1

Type RM Length L Ch R = 1 ,3196.3  ,159.8,156.8,153.9
XS GIS Cut Line= 2
     1723444.834      192715.294     1723537.841      192934.894
#Sta/Elev= 25
     9.9 1277.81    19.9 1271.41    29.8 1265.04    39.7 1258.68    49.7 1252.27
    59.6 1246.22    69.6 1242.02    79.5 1240.26    89.4 1239.88    99.4 1239.78
   109.3 1239.57   119.2 1239.04   129.1 1238.23   129.2 1238.23   139.1  1238.1
   149.1 1238.89     159 1239.73   168.9  1240.3   178.9  1240.6   188.8 1240.67
   198.7 1241.44   208.7 1244.87   218.6 1251.14   228.5 1257.42   238.5 1262.07
#Mann= 3 , 0 , 0
       0      .1       0   129.1    .045       0   149.1      .1       0
Bank Sta=129.1,149.1
XS Rating Curve= 0 ,0
Exp/Cntr=0.3,0.1

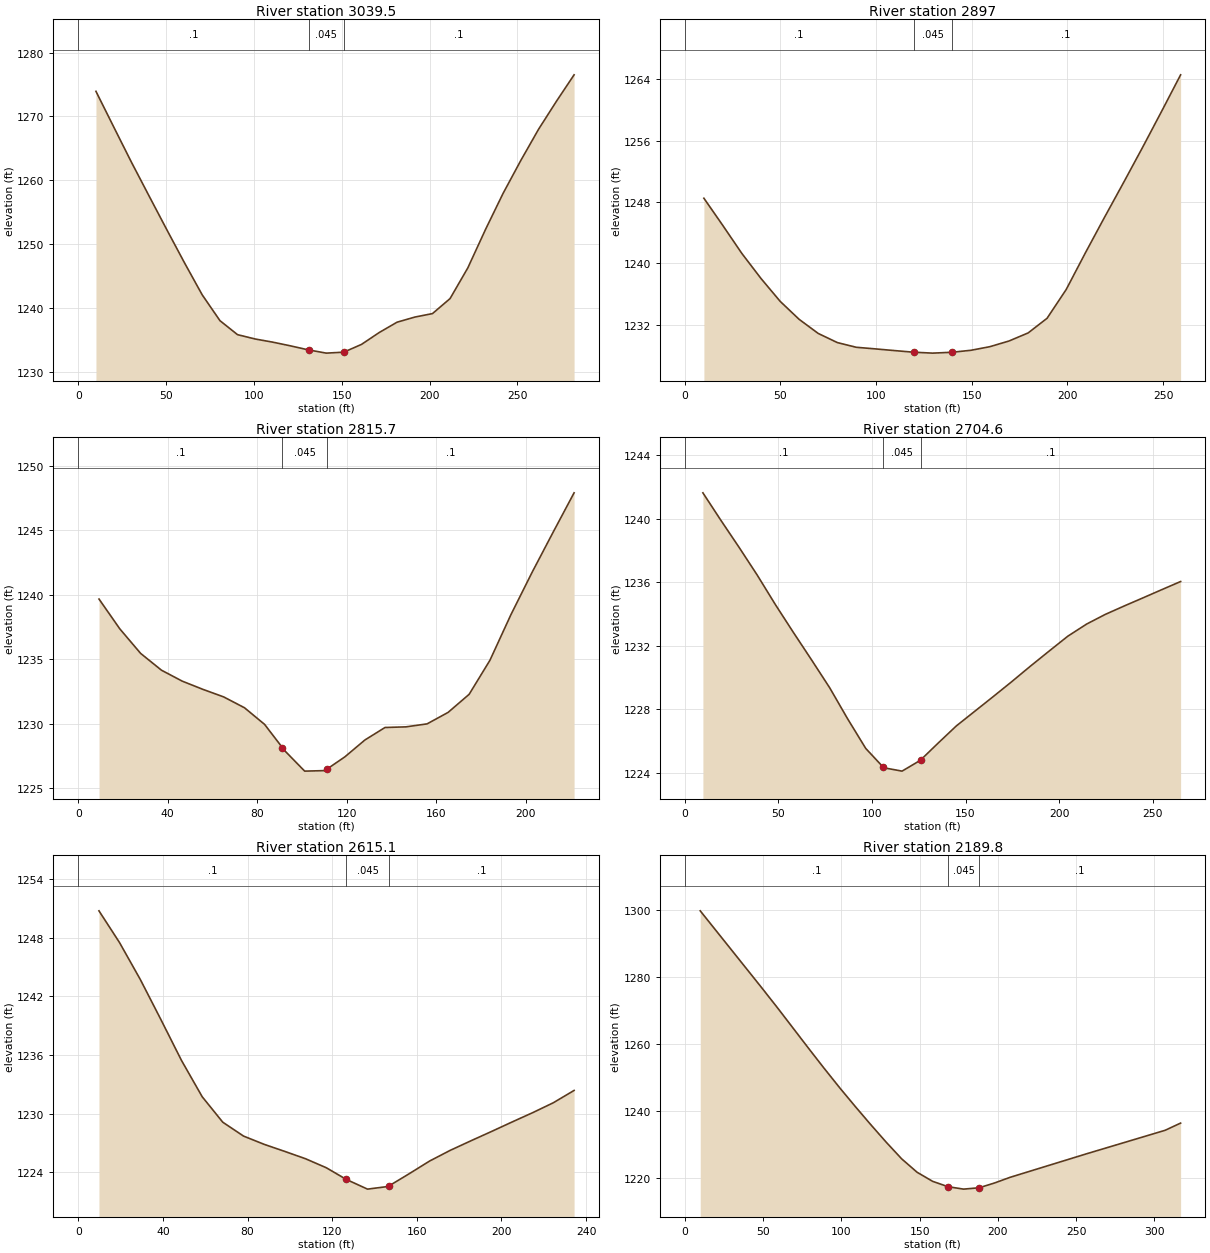
Type RM Length L Ch R = 1 ,3039.5  ,142.6,142.4,142.3
XS GIS Cut Line= 2
     1723288.533      192784.902     1723428.043      193030.337
#Sta/Elev= 29
    10.1 1273.94    20.2 1268.37    30.2  1262.9    40.3 1257.58    50.4  1252.3
    60.5  1247.1    70.6 1242.08    80.7 1238.04    90.7 1235.85   100.8 1235.17
   110.9 1234.67     121 1234.09   131.1 1233.46   131.2 1233.46   141.2 1232.96
   151.2 1233.11   161.3 1234.33   171.4 1236.19   181.5  1237.8   191.6  1238.6
   201.7 1239.15   211.7  1241.5   221.8  1246.3   231.9 1252.33     242 1258.03
   252.1 1263.18   262.1 1268.01   272.2 1272.36   282.3 1276.52
#Mann= 3 , 0 , 0
       0      .1       0   131.2    .045       0   151.2      .1       0
Bank Sta=131.2,151.2
XS Rating Curve= 0 ,0
Exp/Cntr=0.3,0.1

Type RM Length L Ch R = 1 ,2897    ,72.3,81.3,91.5
XS GIS Cut Line= 2
     1723169.691      192864.991     1723298.867      193089.758
#Sta/Elev= 27
      10  1248.5    19.9 1244.95    29.9 1241.29    39.9 1238.03    49.9 1235.06
    59.8 1232.72    69.8 1230.88    79.8 1229.69    89.7 1229.08    99.7 1228.87
   109.7 1228.65   119.6 1228.44   119.7 1228.44   129.6 1228.32   139.6 1228.43
   149.6 1228.69   159.5 1229.16   169.5  1229.9   179.5 1230.95   189.4 1232.86
   199.4 1236.61   209.4 1241.37   219.4    1246   229.3  1250.5   239.3 1255.11
   249.3 1259.83   259.2 1264.57
#Mann= 3 , 0 , 0
       0      .1       0   119.6    .045       0   139.6      .1       0
Bank Sta=119.6,139.6
XS Rating Curve= 0 ,0
Exp/Cntr=0.3,0.1

Type RM Length L Ch R = 1 ,2815.7  ,110.4,111.1,110.6
XS GIS Cut Line= 4
     1723130.577      192916.812      1723157.08      192986.268
     1723174.444      193046.584     1723218.311      193118.781
#Sta/Elev= 26
     9.3 1239.67    18.6 1237.36    27.9 1235.46    37.2 1234.16    46.5 1233.31
    55.8 1232.67      65 1232.09    74.3 1231.25    83.3 1229.96    91.2 1228.17
    92.3 1227.92   101.2 1226.34   110.2 1226.38   111.2  1226.5   119.2 1227.45
   128.1 1228.75   137.1 1229.72   146.5 1229.77   155.9    1230   165.3 1230.89
   174.7 1232.29     184 1234.93   193.4 1238.47   202.8 1241.73   212.2 1244.84
   221.6  1247.9
#Mann= 3 , 0 , 0
       0      .1       0    91.2    .045       0   111.2      .1       0
Bank Sta=91.2,111.2
XS Rating Curve= 0 ,0
Exp/Cntr=0.3,0.1

Type RM Length L Ch R = 1 ,2704.6  ,90.4,89.6,88.8
XS GIS Cut Line= 3
     1723053.432      192934.746     1723076.106      193097.584
     1723113.214      193190.979
#Sta/Elev= 29
     9.7 1241.64    19.3 1239.91      29 1238.21    38.7 1236.46    48.4  1234.6
      58 1232.85    67.7 1231.12    77.4 1229.36      87  1227.4    96.7 1225.53
   106.1 1224.34   106.4 1224.31   116.1  1224.1   125.7 1224.77   126.1 1224.81
   135.4 1225.87   145.1 1226.95   154.7 1227.85   164.4 1228.76   174.5 1229.72
   184.5  1230.7   194.6 1231.66   204.6  1232.6   214.7 1233.37   224.7 1233.98
   234.8 1234.51   244.8 1235.02   254.9 1235.54   264.9 1236.05
#Mann= 3 , 0 , 0
       0      .1       0   106.1    .045       0   126.1      .1       0
Bank Sta=106.1,126.1
XS Rating Curve= 0 ,0
Exp/Cntr=0.3,0.1

Type RM Length L Ch R = 1 ,2615.1  ,426.1,425.3,424.4
XS GIS Cut Line= 2
     1722960.425      192939.913     1722999.892      193170.873
#Sta/Elev= 26
     9.8 1250.76    19.5 1247.52    29.3 1243.75    39.1 1239.62    48.8 1235.45
    58.6 1231.73    68.3 1229.13    78.1 1227.71    87.9 1226.86    97.6 1226.14
   107.4 1225.39   117.2 1224.47   126.7 1223.27   126.9 1223.25   136.7 1222.28
   146.4 1222.55   146.7 1222.59   156.2 1223.83     166 1225.15   175.7 1226.24
   185.5 1227.22   195.3 1228.18     205 1229.15   214.8 1230.11   224.5 1231.12
   234.3 1232.38
#Mann= 3 , 0 , 0
       0      .1       0   126.7    .045       0   146.7      .1       0
Bank Sta=126.7,146.7
XS Rating Curve= 0 ,0
Exp/Cntr=0.3,0.1

Type RM Length L Ch R = 1 ,2189.8  ,292.9,292.1,291.4
XS GIS Cut Line= 2
     1722536.726      192952.831     1722601.315      193262.854
#Sta/Elev= 20
     9.9 1299.68    49.5 1276.55    59.4 1270.67    79.2 1258.62    89.1 1252.68
      99  1246.9   108.9 1241.34   118.8 1235.93   128.7 1230.68   138.5 1225.75
   148.4 1221.73   158.3 1219.03   168.1 1217.43   178.1  1216.7   188.1 1217.11
   197.9 1218.54   207.8 1220.22   257.3 1227.33   306.8 1234.24   316.7 1236.39
#Mann= 3 , 0 , 0
       0      .1       0   168.1    .045       0   188.1      .1       0
Bank Sta=168.1,188.1
XS Rating Curve= 0 ,0
Exp/Cntr=0.3,0.1

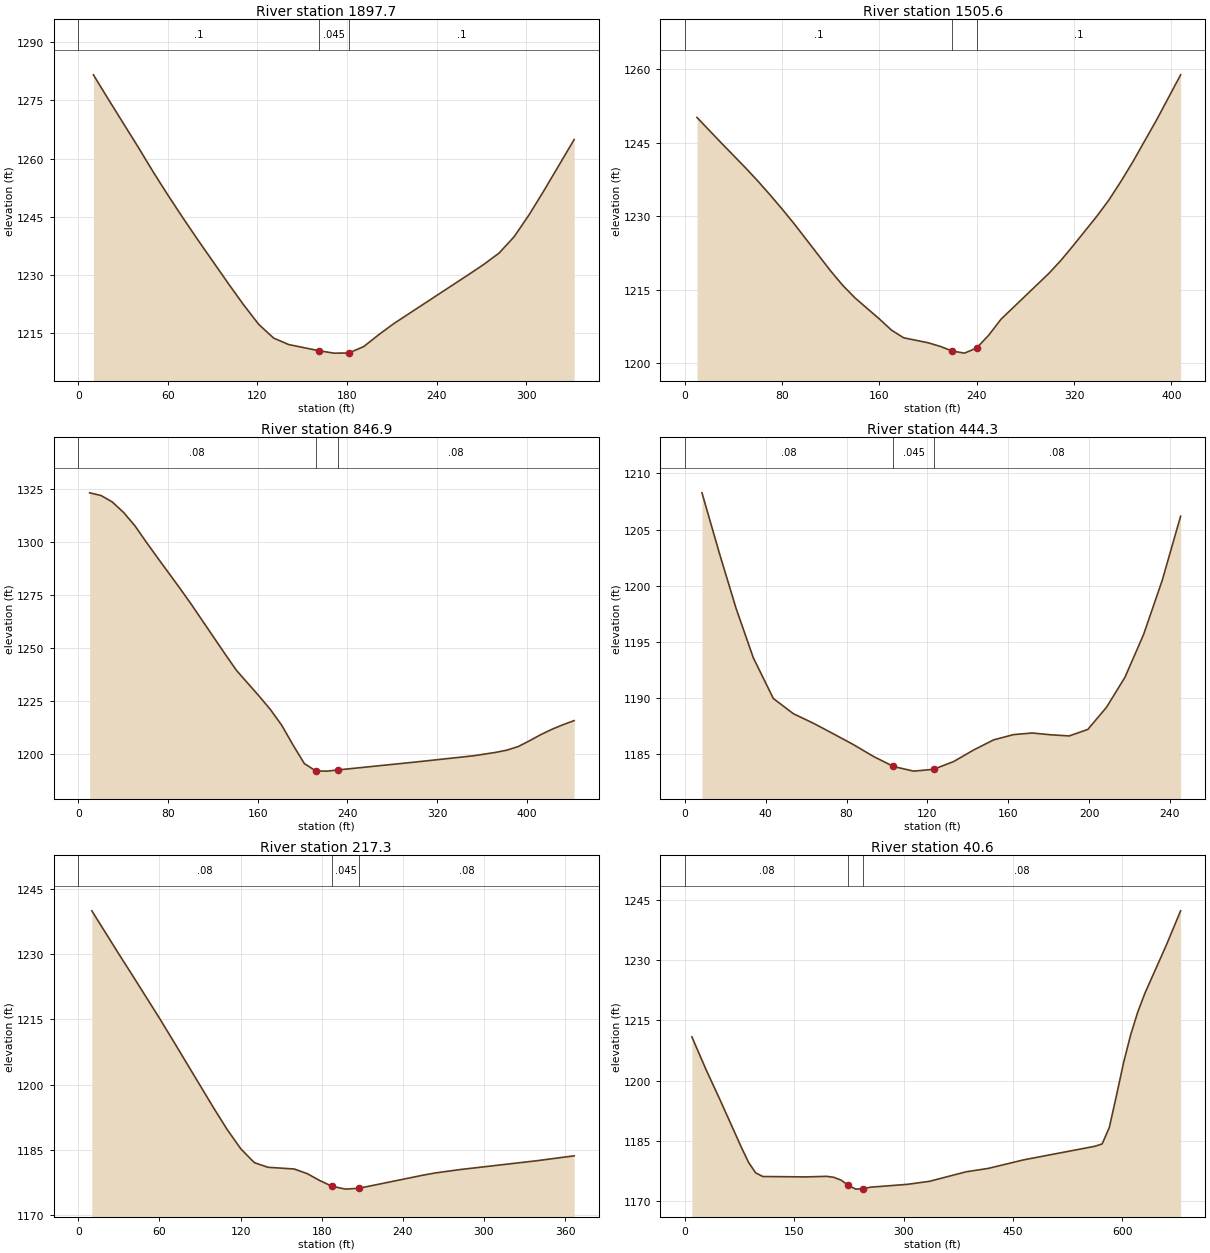
Type RM Length L Ch R = 1 ,1897.7  ,385.5,392.1,398.6
XS GIS Cut Line= 2
     1722255.122      193051.005     1722332.628      193373.946
#Sta/Elev= 25
    10.1 1281.59    20.1  1275.3    40.3 1262.83    50.3 1256.47    60.4 1250.36
    70.4 1244.52    80.5 1238.81   100.6 1227.73   110.7 1222.31   120.8 1217.29
   130.8 1213.74   140.9 1212.07   161.1 1210.48   171.1 1209.86   181.1 1209.88
   191.2 1211.56   201.3 1214.63   211.3 1217.47   261.7 1230.18   271.7 1232.76
   281.8 1235.64   291.9 1239.86   301.9  1245.5     312 1251.83   332.1  1264.9
#Mann= 3 , 0 , 0
       0      .1       0   161.1    .045       0   181.1      .1       0
Bank Sta=161.1,181.1
XS Rating Curve= 0 ,0
Exp/Cntr=0.3,0.1

Type RM Length L Ch R = 1 ,1505.6  ,662.3,658.7,655.2
XS GIS Cut Line= 3
     1721955.433      193128.511     1721959.764       193388.38
      1722044.88      193509.011
#Sta/Elev= 29
      10 1250.14      30 1244.93      50 1239.83      60 1237.16      70 1234.35
      80 1231.43      90 1228.39     120 1218.75     130  1215.8   139.9 1213.29
   159.9 1208.99   169.9  1206.7   179.9 1205.14   199.9 1204.13   209.9 1203.39
   219.9 1202.43   229.9 1202.01   239.9 1203.06   249.9 1205.71   259.9 1208.94
   299.3 1218.31   309.1 1220.94     319  1223.9   338.6 1229.95   348.5 1233.26
   358.3 1237.02   368.2 1241.06   387.9  1249.7   407.5 1258.84
#Mann= 3 , 0 , 0
       0      .1       0   219.9    .045       0   239.9      .1       0
Bank Sta=219.9,239.9
XS Rating Curve= 0 ,0
Exp/Cntr=0.3,0.1

Type RM Length L Ch R = 1 ,846.9   ,410.6,402.6,396.8
XS GIS Cut Line= 4
      1721374.93      193158.476     1721314.684      193286.023
     1721341.344      193445.248      1721418.85      193561.506
#Sta/Elev= 29
    10.1 1323.07    20.2 1321.81    30.2 1318.79    40.3 1313.85    50.4 1307.58
    60.5 1299.91    70.5 1292.57    90.7 1277.97   100.8 1270.45     131 1246.95
   141.1 1239.29   161.2 1227.22   171.3 1220.86   181.4 1213.45   191.5 1204.12
   201.6 1195.35   211.8  1191.9   221.8 1191.81   231.8 1192.39   302.5  1196.2
   352.4 1199.04   372.4 1200.66   382.3 1201.72   392.3  1203.4   402.3  1206.1
   412.3 1208.99   422.3 1211.52   432.2 1213.69   442.2 1215.64
#Mann= 3 , 0 , 0
       0     .08       0   211.8    .045       0   231.8     .08       0
Bank Sta=211.8,231.8
XS Rating Curve= 0 ,0
Exp/Cntr=0.3,0.1

Type RM Length L Ch R = 1 ,444.3   ,227.1,227,224.5
XS GIS Cut Line= 4
     1720994.823      193477.939     1721000.681      193511.352
     1721046.423      193631.728     1721115.457      193677.166
#Sta/Elev= 28
     8.5 1208.27      17 1202.97    25.4 1197.98    33.9  1193.6    43.8 1189.98
    53.7 1188.63    63.6 1187.78    73.5 1186.84    83.5 1185.87    93.4 1184.82
   103.2 1183.94   103.3 1183.93   113.2 1183.52   123.1 1183.68   123.2 1183.69
     133 1184.37   142.9  1185.4   152.8  1186.3   162.7 1186.77   171.9 1186.91
   181.1 1186.75   190.2 1186.65   199.4 1187.23   208.6 1189.19   217.8 1191.88
     227 1195.68   236.2 1200.49   245.3 1206.19
#Mann= 3 , 0 , 0
       0     .08       0   103.2    .045       0   123.2     .08       0
Bank Sta=103.2,123.2
XS Rating Curve= 0 ,0
Exp/Cntr=0.3,0.1

Type RM Length L Ch R = 1 ,217.3   ,193.7,176.7,158.9
XS GIS Cut Line= 4
     1720816.282      193472.003     1720805.948      193621.848
     1720856.826      193723.775     1720953.209      193758.775
#Sta/Elev= 21
      10 1239.99      30 1230.03    40.1 1225.12    60.1 1215.23    70.1 1210.13
   100.1 1194.62   110.1 1189.66   120.2 1185.21   130.2 1182.04   140.2 1180.98
   159.7 1180.58   169.2 1179.53   178.7  1177.9   187.7  1176.6   197.7 1175.95
   207.7 1176.16   254.6 1179.14   264.1 1179.68   282.8 1180.47   338.7 1182.47
   366.7 1183.61
#Mann= 3 , 0 , 0
       0     .08       0   187.7    .045       0   207.7     .08       0
Bank Sta=187.7,207.7
XS Rating Curve= 0 ,0
Exp/Cntr=0.3,0.1

Type RM Length L Ch R = 1 ,40.6    ,23.2,40.6,58.8
XS GIS Cut Line= 4
     1720650.751      193482.454     1720621.044      193684.478
     1720794.682      193787.747     1721066.699      193818.313
#Sta/Elev= 30
     9.7 1210.88    29.2 1202.71    48.6  1195.1    77.8 1183.31    87.5 1179.63
    97.2 1177.04     107 1176.13   165.3 1176.03   194.5 1176.17   204.2 1175.94
   214.3 1175.23   224.5  1173.9   234.5 1172.99   244.5  1173.1   254.7 1173.47
   305.2 1174.18   335.5 1174.93     386 1177.31     416 1178.14   464.9 1180.28
   562.6 1183.66   572.4 1184.24   582.2 1188.34     592 1196.27   601.7 1204.42
   611.5 1211.39   621.3  1217.1   631.1 1221.77   660.4 1233.71     680 1242.24
#Mann= 3 , 0 , 0
       0     .08       0   224.5    .045       0   244.5     .08       0
Bank Sta=224.5,244.5
XS Rating Curve= 0 ,0
Exp/Cntr=0.3,0.1

Chan Stop Cuts=-1
Use User Specified Reach Order=0